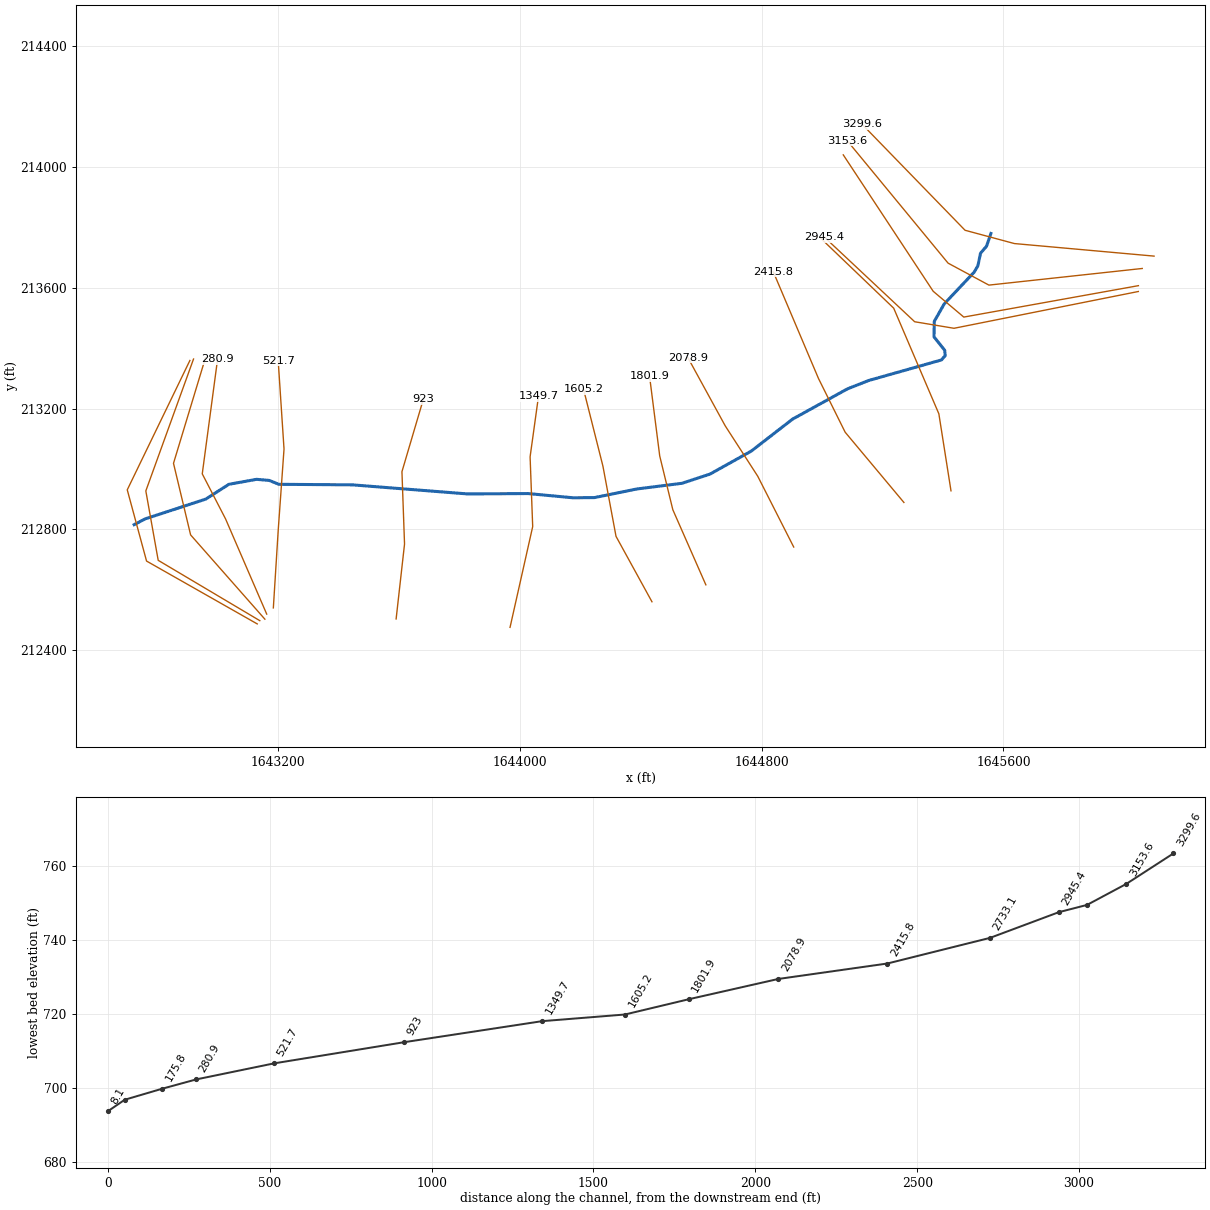
--- lckfrk.prj (project) ---

Proj Title=lckfrk
Current Plan=p01
Default Exp/Contr=0,0
English Units
Geom File=g01
Flow File=f01
Plan File=p01
BEGIN DESCRIPTION:
END DESCRIPTION:
DSS Export Rating Curves= 0
DSS Export Rating Curve Sorted= 0
DSS Export Volume Flow Curves= 0
DXF OffsetX= 0
DXF OffsetY= 0
DXF ScaleX= 0
DXF ScaleY= 0

--- lckfrk.p01 (plan) ---

Plan Title=Floodplain
Program Version=4.00
Geom File=g01
Flow File=f01
K Sum by GR=0
Std Step Tol=0.01
Critical Tol=0.01
Num of Std Step Trials=20
Max Error Tol=0.3
Flow Tol Ratio=0.001
Split Flow NTrial=30
Split Flow Tol=0.02
Split Flow Ratio=0.02
Log Output Level=0
Friction Slope Method=1
Unsteady Friction Slope Method=2
Unsteady Bridges Friction Slope Method=1
Global Log Level=0
CheckData=False
Run HTab=0
Run UNet=0
Run PostProcess=0
UNET Theta=0
UNET Theta Warmup=0
UNET ZTol=0
UNET ZSATol=0
UNET MxIter=0
UNET MaxInSteps=0
UNET DtIC=0
UNET DtMin=0
UNET MaxCRTS=0
UNET WFStab=0
UNET SFStab=0
UNET WFX=0
UNET SFX=0
UNET DSS MLevel=0
UNET DZMax Abort=0
UNET Convert EG Bridges=0
UNET Use Existing IB Tables=0
UNET Froude Limit=0
UNET Froude Power=0
Write IC File=0
Echo Input=False
Echo Output=False
Write Detailed=0

--- lckfrk.f01 (steady flow) ---

Flow Title=NFF Regression Equation
Program Version=4.00
Number of Profiles= 1
Profile Names=P100yr
River Rch & RM=lckfrk,Main            ,3299.6
     355
River Rch & RM=lckfrk,Main            ,3032.7
     358
River Rch & RM=lckfrk,Main            ,2415.8
    1160
River Rch & RM=lckfrk,Main            ,280.9
    1221
Boundary for River Rch & Prof#=lckfrk,Main            , 1
Up Type= 0
Dn Type= 3
Dn Slope=0.014
DSS Import GetInterval= 0
DSS Import GetPeak= 0
DSS Import FillOption= 0

--- lckfrk.g01 (geometry) ---

Geom Title=USGS 10m DEM
Program Version=4.00

River Reach=lckfrk          ,Main
Reach XY= 30
     1645558.487      213780.212     1645543.938       213737.96
     1645524.082      213714.879     1645515.513      213673.339
     1645503.322      213652.343       1645404.2       213547.04
     1645371.253       213489.12     1645370.248      213437.647
     1645405.794      213392.947     1645407.149      213375.338
     1645394.958      213361.115     1645154.581      213293.099
     1645084.145       213265.33     1644902.635      213165.094
     1644766.503      213059.439     1644629.693      212982.907
     1644536.906      212952.429     1644387.229      212933.465
      1644247.71       212905.02     1644176.596      212904.343
     1644027.552      212918.372     1643828.202      212917.095
     1643447.017      212947.199     1643203.355      212949.031
      1643172.21      212961.855     1643130.073      212965.519
      1643038.47      212949.031     1642961.922      212899.966
     1642761.768      212834.499      1642725.19      212815.291

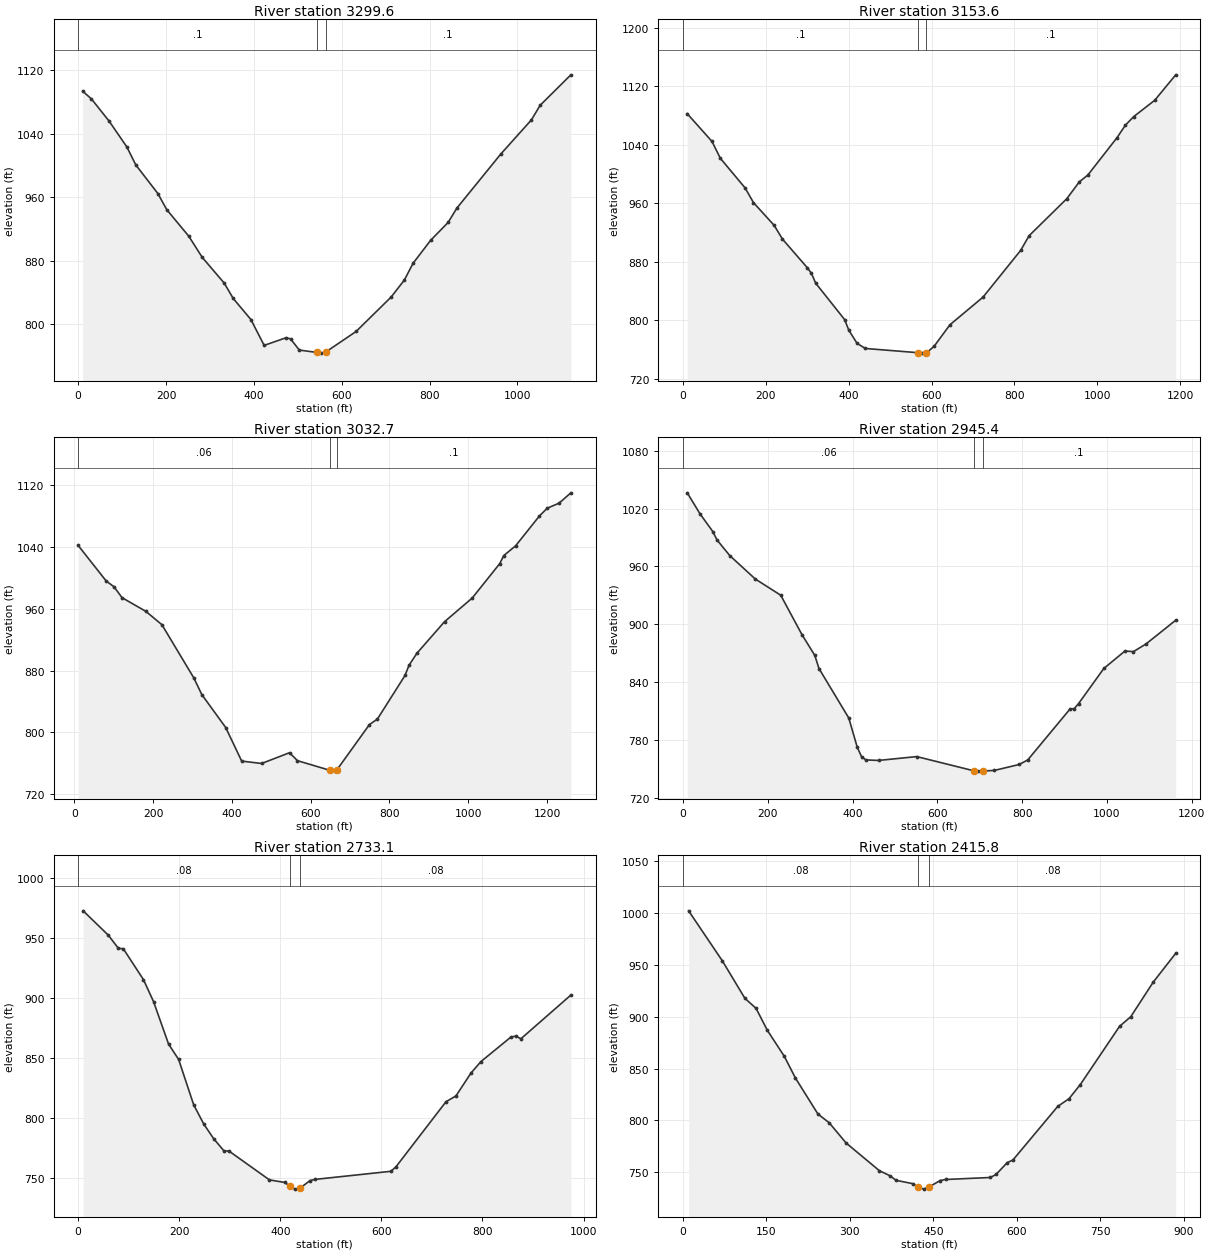
Type RM Length L Ch R = 1 ,3299.6  ,151.2,145.9,140.5
XS GIS Cut Line= 4
     1646098.051      213705.204       1645636.2      213746.794
     1645473.018      213790.825     1645132.675      214141.871
#Sta/Elev= 30
    10.1  1093.6    30.2 1083.71    70.6 1055.64   110.9 1023.18   131.1 1000.66
   181.5  964.49   201.6  944.26     252  910.66   282.3  884.22   332.7  851.58
   352.8  832.49   393.2  805.83   423.4  773.25   473.7  782.96   483.6  781.38
   503.5  767.33   543.2  764.41   553.2   763.5   563.2  764.74   632.7  790.77
   712.6  834.23   742.5   855.5   762.5  876.74   802.4  905.61   842.3  928.17
   862.2  946.26     962 1014.21  1031.9 1057.35  1051.8 1075.76  1121.7 1114.08
#Mann= 3 , 0 , 0
       0      .1       0   543.2    .045       0   563.2      .1       0
Bank Sta=543.2,563.2
XS Rating Curve= 0 ,0
Exp/Cntr=0.3,0.1

Type RM Length L Ch R = 1 ,3153.6  ,126.3,121,115.6
XS GIS Cut Line= 4
     1646058.987      213664.267     1645551.835      213609.136
     1645416.829      213681.926     1645082.907      214088.091
#Sta/Elev= 30
      10 1082.76      70 1044.69      90 1021.78     150  981.04     170  961.12
   220.1  929.89   240.1  911.14   300.1  871.95   310.1  864.27   320.1  851.01
   390.1  801.12   400.1  786.71   420.1  768.65   440.1  761.59   567.2  755.84
   577.2  755.23   587.2  755.36     606  764.48   644.3  793.99   724.2  831.82
   815.2  895.83   835.4   915.8   926.4  966.41   956.8  989.54     977  998.62
  1047.8 1049.98    1068 1067.09  1088.2 1078.78  1138.8 1101.06  1189.3 1135.79
#Mann= 3 , 0 , 0
       0      .1       0   567.2    .045       0   587.2      .1       0
Bank Sta=567.2,587.2
XS Rating Curve= 0 ,0
Exp/Cntr=0.3,0.1

Type RM Length L Ch R = 1 ,3032.7  ,73.8,87.3,100.8
XS GIS Cut Line= 4
     1646046.296      213607.305     1645468.756       213503.18
     1645367.616      213588.667     1645070.217      214040.761
#Sta/Elev= 30
    10.1 1042.17    80.9  996.25   101.2  988.47   121.4  974.46   182.1  956.63
   222.6   939.4   303.5  870.44   323.8  848.84   384.5  806.07     425  762.57
   475.6  759.47   546.4   773.4   566.6  763.11   649.2  750.57   662.5  749.56
  665.87  750.68   749.3  809.97   769.4  817.06   839.5  873.59   849.6  886.75
   869.6  902.34   939.7  943.27  1009.9  973.93    1080  1018.7  1090.1 1029.04
  1120.1 1041.66  1180.3 1080.22  1200.3 1090.43  1230.4 1096.99  1260.4 1110.39
#Mann= 3 , 0 , 0
    10.1     .06       0   649.2    .045       0  665.87      .1       0
Bank Sta=649.2,665.87
XS Rating Curve= 0 ,0
Exp/Cntr=0.3,0.1

Type RM Length L Ch R = 1 ,2945.4  ,238.9,212.3,185.6
XS GIS Cut Line= 4
      1646045.97      213587.939     1645436.422       213466.03
     1645306.385      213487.703     1645008.384      213767.643
#Sta/Elev= 30
      10 1036.27    40.1  1014.5    70.2  996.15    80.2  987.41   110.3  971.17
   170.4  946.92   230.6  930.03   280.7  889.08   310.8  867.73   320.8     854
     391  802.71   411.1  772.28   421.1  762.67   431.1  759.24   461.2  758.68
   551.4  762.67     687  747.83     697  747.59     707  747.72   734.6  748.33
   793.3   754.5   813.3  759.23     913  812.04     923  812.47     933  817.58
   992.8  854.12  1042.6  872.18  1062.6  871.54  1092.5  879.59  1162.3  904.11
#Mann= 3 , 0 , 0
       0     .06       0     687    .045       0     707      .1       0
Bank Sta=687,707
XS Rating Curve= 0 ,0
Exp/Cntr=0.3,0.1

Type RM Length L Ch R = 1 ,2733.1  ,315.9,317.3,318.6
XS GIS Cut Line= 4
     1645426.462      212927.391     1645386.327      213182.649
     1645237.025      213532.624     1644994.611      213765.407
#Sta/Elev= 30
     9.9  972.46    59.6  952.18    79.5  941.27    89.4  940.83   129.2  915.15
   149.1  896.89   178.9  861.44   198.8  848.64   228.6  810.85   248.5  794.86
   268.4   782.5   288.4  772.55   298.4  772.37   378.5  748.33   408.6  746.21
   418.6  743.19   428.6  740.64   438.6   741.3   458.7  747.74   468.7  748.74
   618.9  755.49   628.9  759.26   727.8  813.42   747.6   818.3   777.3  837.33
     797  846.89   856.4  867.35   866.2  868.09   876.1  865.88     975   902.3
#Mann= 3 , 0 , 0
       0     .08       0   418.6    .045       0   438.6     .08       0
Bank Sta=418.6,438.6
XS Rating Curve= 0 ,0
Exp/Cntr=0.3,0.1

Type RM Length L Ch R = 1 ,2415.8  ,334,336.8,339.7
XS GIS Cut Line= 4
     1645270.738      212888.862     1645076.486      213121.644
     1644988.189      213299.842     1644838.888      213653.029
#Sta/Elev= 30
    10.1 1002.14    70.7  953.89   111.2  917.78   131.4     908   151.6  886.86
   181.9  861.95   202.1  840.83   242.5  806.13   262.8  797.69   293.1  778.21
   352.9   751.5   372.8  746.39   382.7  742.23   412.6  739.01   422.5   735.7
   432.5   733.7   442.5  735.93   462.3  742.01   472.2     743   552.5  744.93
   562.6  747.88   582.8   759.3   592.9  761.77   673.6  813.56   693.8  820.95
     714  834.53   784.6  890.73   804.8  900.07   845.1  933.36   885.5  961.16
#Mann= 3 , 0 , 0
       0     .08       0   422.5    .045       0   442.5     .08       0
Bank Sta=422.5,442.5
XS Rating Curve= 0 ,0
Exp/Cntr=0.3,0.1

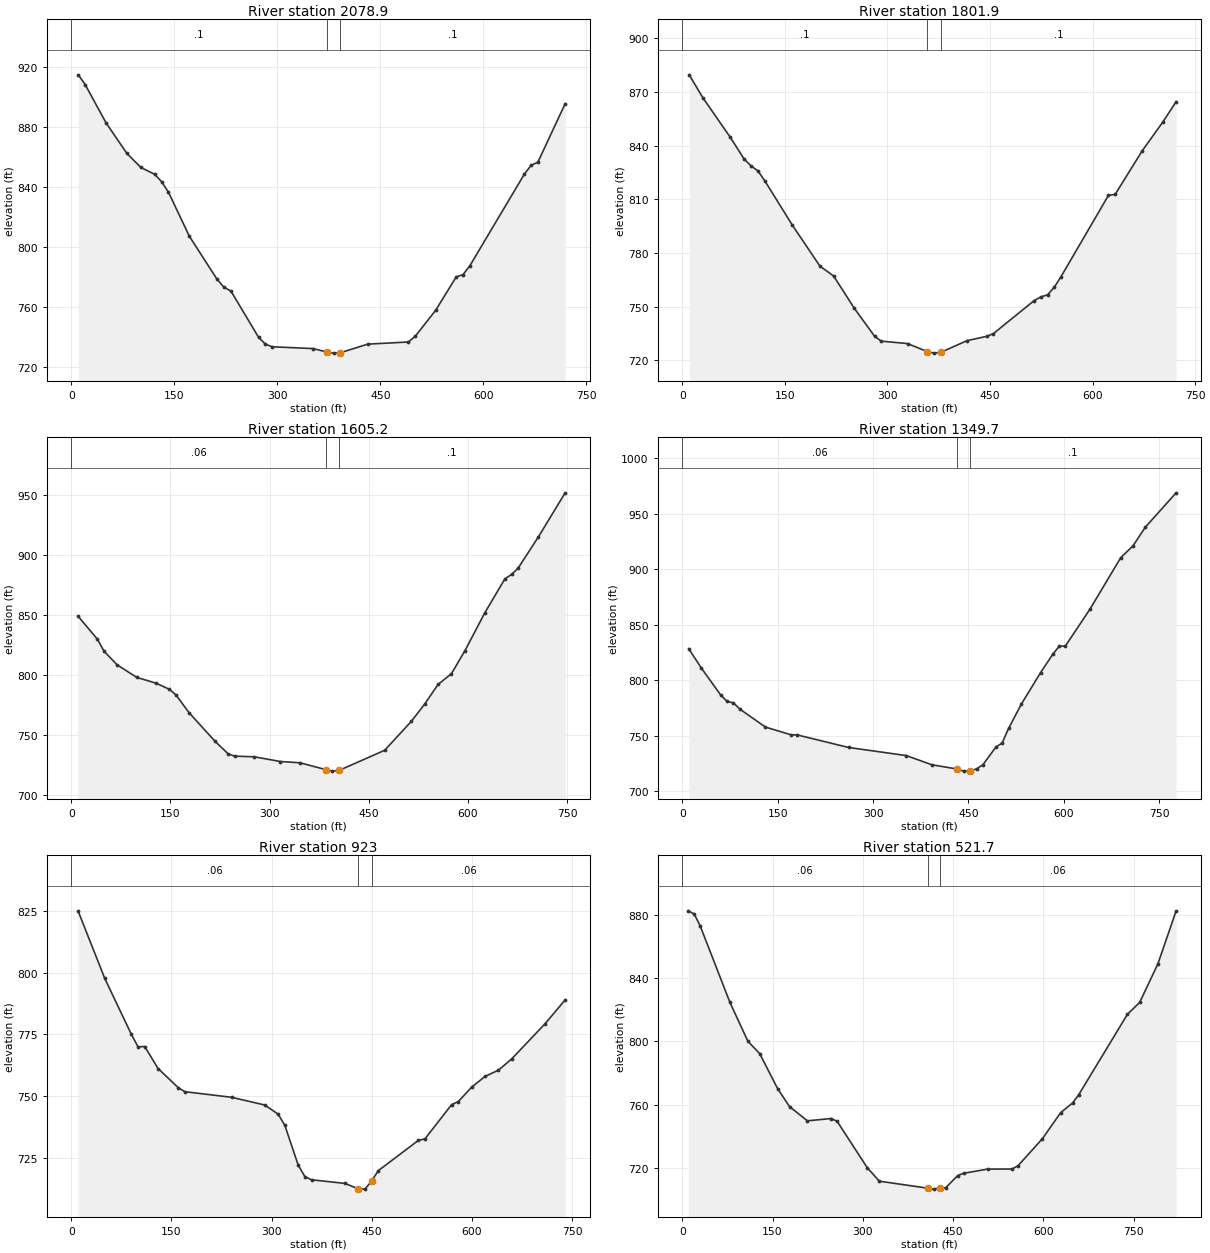
Type RM Length L Ch R = 1 ,2078.9  ,285.4,277.1,268.7
XS GIS Cut Line= 4
     1644906.314      212741.165     1644787.515      212975.553
     1644679.954      213142.514     1644556.338      213368.874
#Sta/Elev= 30
    10.1  914.84    20.2  908.29    50.5  882.88    80.9  862.51   101.1  853.21
   121.3  848.62   131.4  843.73   141.5  836.64   171.8  807.43   212.2  778.71
   222.3   773.4   232.5  770.83   272.7  740.08   282.6  735.52   292.6  733.74
   352.1  732.56   371.9   730.3   381.9  729.52   391.9  729.79   431.6   735.5
   491.1  736.95   501.1  740.82   530.8  758.13   560.6  780.27   570.5  781.78
   580.4  787.63   659.8  848.66   669.7  854.58   679.6  856.68   719.3  895.61
#Mann= 3 , 0 , 0
       0      .1       0   371.9    .045       0   391.9      .1       0
Bank Sta=371.9,391.9
XS Rating Curve= 0 ,0
Exp/Cntr=0.3,0.1

Type RM Length L Ch R = 1 ,1801.9  ,198,196.6,195.3
XS GIS Cut Line= 4
     1644615.738      212615.945     1644506.571      212864.781
     1644463.226      213042.979     1644429.512      213307.869
#Sta/Elev= 30
    10.1  879.67    30.2  866.78    70.4  844.62    90.6  832.48   100.6  828.73
   110.7  825.93   120.8  820.33     161  795.58   201.3   772.7   221.4  767.13
   251.6  749.09   281.4  733.37     291  730.73   329.6  729.35   358.3  724.88
   368.3  724.02   378.3  724.51   416.5     731   445.5  733.43   455.1  734.96
   514.5  753.36   524.4  755.49   534.2  756.61   544.1  760.91     554  766.84
   623.3  812.26   633.1  812.82   672.7   837.2   702.4  853.04   722.2  864.61
#Mann= 3 , 0 , 0
       0      .1       0   358.3    .045       0   378.3      .1       0
Bank Sta=358.3,378.3
XS Rating Curve= 0 ,0
Exp/Cntr=0.3,0.1

Type RM Length L Ch R = 1 ,1605.2  ,259.2,255.5,251.8
XS GIS Cut Line= 4
     1644437.539      212559.756      1644318.74      212776.484
     1644275.394      213009.266     1644211.179      213264.524
#Sta/Elev= 30
     9.9  849.13    39.5  829.69    49.4   819.8    69.2  808.42    98.9  797.99
   128.5  793.09   148.3  788.05   158.2  783.44   177.9   768.7   217.5  744.69
   237.3  734.24   247.2  732.36   276.8  731.85   316.2   727.9   345.8  726.87
   385.1  721.12   395.1   719.9   405.1  720.51   474.1  737.28   514.3   761.3
   534.6  775.78   554.8  792.07     575  801.01   595.3  820.01   625.7  851.89
     656  880.09   666.2  883.73   676.3  889.22   706.7  915.05   747.1  951.68
#Mann= 3 , 0 , 0
       0     .06       0   385.1    .045       0   405.1      .1       0
Bank Sta=385.1,405.1
XS Rating Curve= 0 ,0
Exp/Cntr=0.3,0.1

Type RM Length L Ch R = 1 ,1349.7  ,426.8,426.8,426.7
XS GIS Cut Line= 4
     1643968.229      212474.938     1644043.148      212808.859
     1644034.586      213040.036     1644062.412      213241.245
#Sta/Elev= 30
    10.1   828.5    30.2  810.87    60.4  786.72    70.5  780.98    80.5  779.66
    90.6  774.02   130.8  757.81   171.1  750.86   181.2  750.69   261.7  739.42
   352.3  732.13   392.5  723.86   432.8  719.94   442.8   718.1   452.8  718.15
   462.9  720.18     473  723.93   493.1  739.69   503.2  743.54   513.2  756.57
   533.3  778.52   563.5  806.85   583.2  823.87   592.9  830.67   602.6  830.96
   641.3  864.19   689.6  910.54     709  921.27   728.3  938.03   776.7  969.03
#Mann= 3 , 0 , 0
       0     .06       0   432.8    .045       0   452.8      .1       0
Bank Sta=432.8,452.8
XS Rating Curve= 0 ,0
Exp/Cntr=0.3,0.1

Type RM Length L Ch R = 1 ,923     ,404,401.3,398.6
XS GIS Cut Line= 4
     1643591.497      212502.765     1643619.324      212751.065
     1643610.762      212990.804     1643681.399      213230.543
#Sta/Elev= 30
      10  825.05      50  797.71    89.9  775.04    99.9     770   109.9  770.13
   129.9  761.22   159.9  753.52   169.9  751.84   239.9  749.58   289.8  746.44
   309.8  742.74   319.8  738.21   339.8  722.14   349.8  717.46   359.8  716.18
   409.8  714.72   429.8  712.52   439.8   712.4   449.8  715.69   459.8  719.88
   519.7   732.1   529.7  732.75   569.7  746.63   579.7  747.84   599.7   753.7
   619.7  758.02   639.7  760.54   659.7  765.13   709.7  779.37   739.7  788.99
#Mann= 3 , 0 , 0
       0     .06       0   429.8    .045       0   449.8     .06       0
Bank Sta=429.8,449.8
XS Rating Curve= 0 ,0
Exp/Cntr=0.3,0.1

Type RM Length L Ch R = 1 ,521.7   ,227,240.8,254.5
XS GIS Cut Line= 4
     1643185.485      212539.417     1643201.539       212796.28
     1643220.804      213065.986     1643201.539      213358.167
#Sta/Elev= 30
     9.9  882.54    19.8  880.55    29.7  873.05    79.2  824.65   108.9   800.2
   128.7  792.27   158.4  770.19   178.2  758.85   207.9  749.84   247.5  751.31
   257.4  749.51   307.4  720.19   327.5  711.69   407.6  707.31   417.6  706.68
   427.6  707.43   437.6  707.51   457.7  715.25   467.7  716.72   507.7  719.35
     548  719.37     558  721.48   598.4  738.53   628.7  754.94   648.9  761.25
     659  766.46   739.8  817.19     760  824.62   790.3  848.98   820.6  882.45
#Mann= 3 , 0 , 0
       0     .06       0   407.6    .045       0   427.6     .06       0
Bank Sta=407.6,427.6
XS Rating Curve= 0 ,0
Exp/Cntr=0.3,0.1

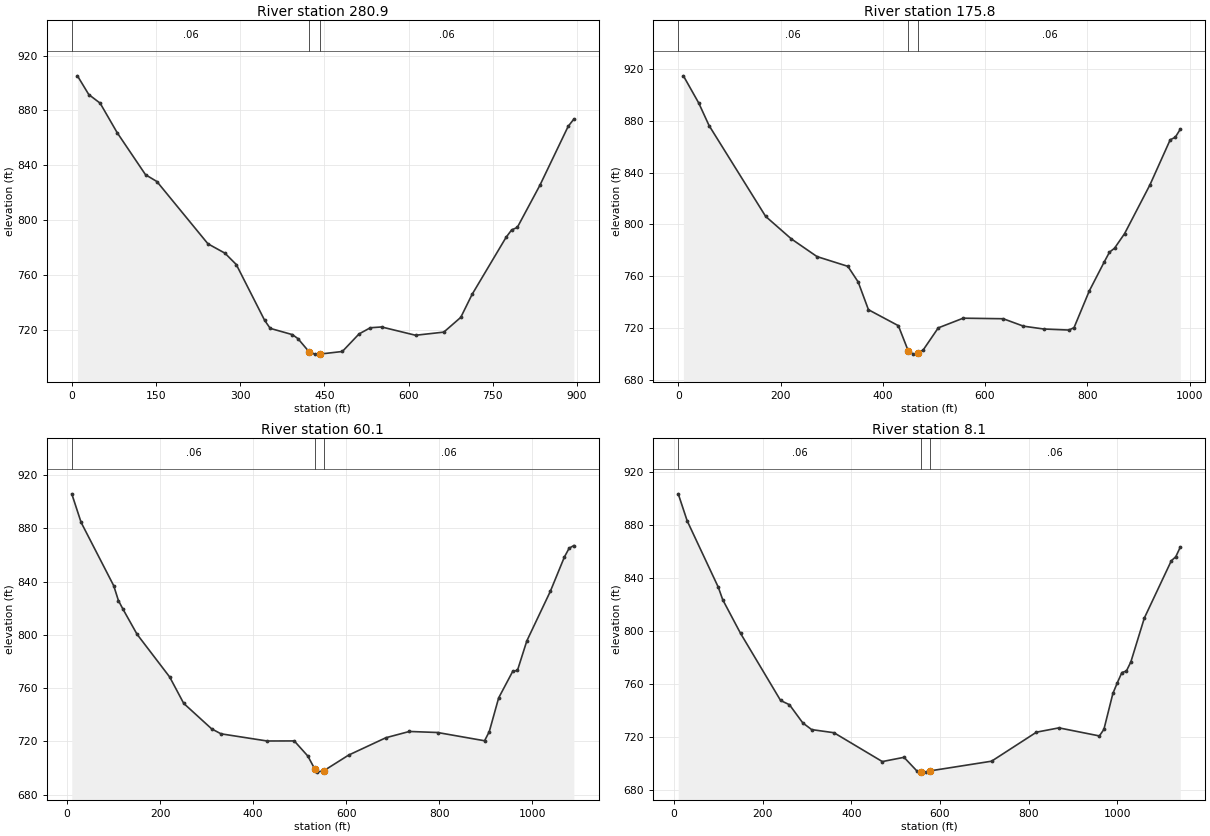
Type RM Length L Ch R = 1 ,280.9   ,111.2,105.2,99.1
XS GIS Cut Line= 4
     1643163.526      212518.885     1643027.469      212834.345
      1642950.41      212983.647      1643000.98      213362.921
#Sta/Elev= 30
    10.1  905.28    30.3  891.62    50.5  885.35    80.8  863.86   131.4  833.15
   151.6   828.2   242.5  782.79   272.8  775.95     293  767.67   343.5  726.98
   353.4  721.12     393  716.54   402.8  713.64   422.5  704.12   432.5  702.33
   442.5  702.39   481.9  704.26   511.6  717.04   531.7  721.56   551.8  722.14
   612.3  716.09   662.6  718.38   692.8  729.14   712.9  745.84   773.4  787.44
   783.4  792.91   793.5  794.73   833.8  825.51   884.1  868.45   894.2   873.7
#Mann= 3 , 0 , 0
       0     .06       0   422.5    .045       0   442.5     .06       0
Bank Sta=422.5,442.5
XS Rating Curve= 0 ,0
Exp/Cntr=0.3,0.1

Type RM Length L Ch R = 1 ,175.8   ,117.1,115.6,114.2
XS GIS Cut Line= 4
     1643157.506      212502.029      1642911.88      212781.367
      1642855.29      213018.564     1642961.246      213368.941
#Sta/Elev= 30
    10.1  914.83    40.2  893.73    60.3  876.41   170.9  806.25   221.2  788.84
   271.4  775.17   331.8  767.63   351.9  755.56     372  734.12   430.5  721.78
   449.8  702.34   459.8  699.81   469.8  700.59   479.3  703.17   508.5  720.09
   557.3  727.58   635.6  727.15   675.2  721.41   714.8  719.22   764.2  718.41
   774.1  720.31   803.8  748.56   833.5  771.33   843.4   778.6   853.3  781.66
     873  792.97   922.5  830.58   962.1  865.41     972  867.34   981.9  873.62
#Mann= 3 , 0 , 0
       0     .06       0   449.8    .045       0   469.8     .06       0
Bank Sta=449.8,469.8
XS Rating Curve= 0 ,0
Exp/Cntr=0.3,0.1

Type RM Length L Ch R = 1 ,60.1    ,49.9,52,54.1
XS GIS Cut Line= 4
     1643140.649      212497.212      1642804.72      212697.084
     1642763.783      212927.057     1642921.513      213364.125
#Sta/Elev= 30
      10  905.99    30.1   884.5   100.2   836.9   110.3  825.73   120.3  819.16
   150.3  800.45   220.5  768.29   250.6  748.49   310.7  729.34   330.8  725.62
   429.8  720.23   488.2  720.28   517.4   708.9  532.69  698.89   536.9  696.83
  552.37  698.02     605  709.62   685.1  722.68   735.6  727.39   796.2  726.61
   897.2   720.4   907.3  727.25   927.5  752.62   957.8  772.61   967.9  773.28
   988.1  795.51  1038.6  832.74  1068.9  858.59    1079  865.13  1089.1  867.13
#Mann= 3 , 0 , 0
      10     .06       0  532.69    .045       0  552.37     .06       0
Bank Sta=532.69,552.37
XS Rating Curve= 0 ,0
Exp/Cntr=0.3,0.1

Type RM Length L Ch R = 1 ,8.1     ,9.2,8.1,7.1
XS GIS Cut Line= 4
     1643132.221      212486.376     1642766.191      212694.676
     1642702.376      212930.669     1642909.472      213359.309
#Sta/Elev= 30
      10  903.24    30.1  882.93   100.3  832.93   110.3  823.49   150.4  798.23
   240.7  747.67   260.7  744.46   290.8  730.75   310.8  725.73     361  723.39
     470  701.67   518.9  704.87   548.3  694.48   557.8  694.03   567.8  693.72
   577.8  694.67   716.3  701.95   817.5  723.81   868.2  727.04   959.3  720.97
   969.5  725.93   989.7  752.93   999.9  761.13    1010  768.69  1020.1  769.78
  1030.2  776.69  1060.6  809.73  1121.4  852.83  1131.5  855.88  1141.7  863.17
#Mann= 3 , 0 , 0
      10     .06       0   557.8    .045       0   577.8     .06       0
#XS Ineff= 2 , 0
       0                     615       0
Permanent Ineff=
       F       F
Bank Sta=557.8,577.8
XS Rating Curve= 0 ,0
Exp/Cntr=0.3,0.1

Chan Stop Cuts=-1
Use User Specified Reach Order=0